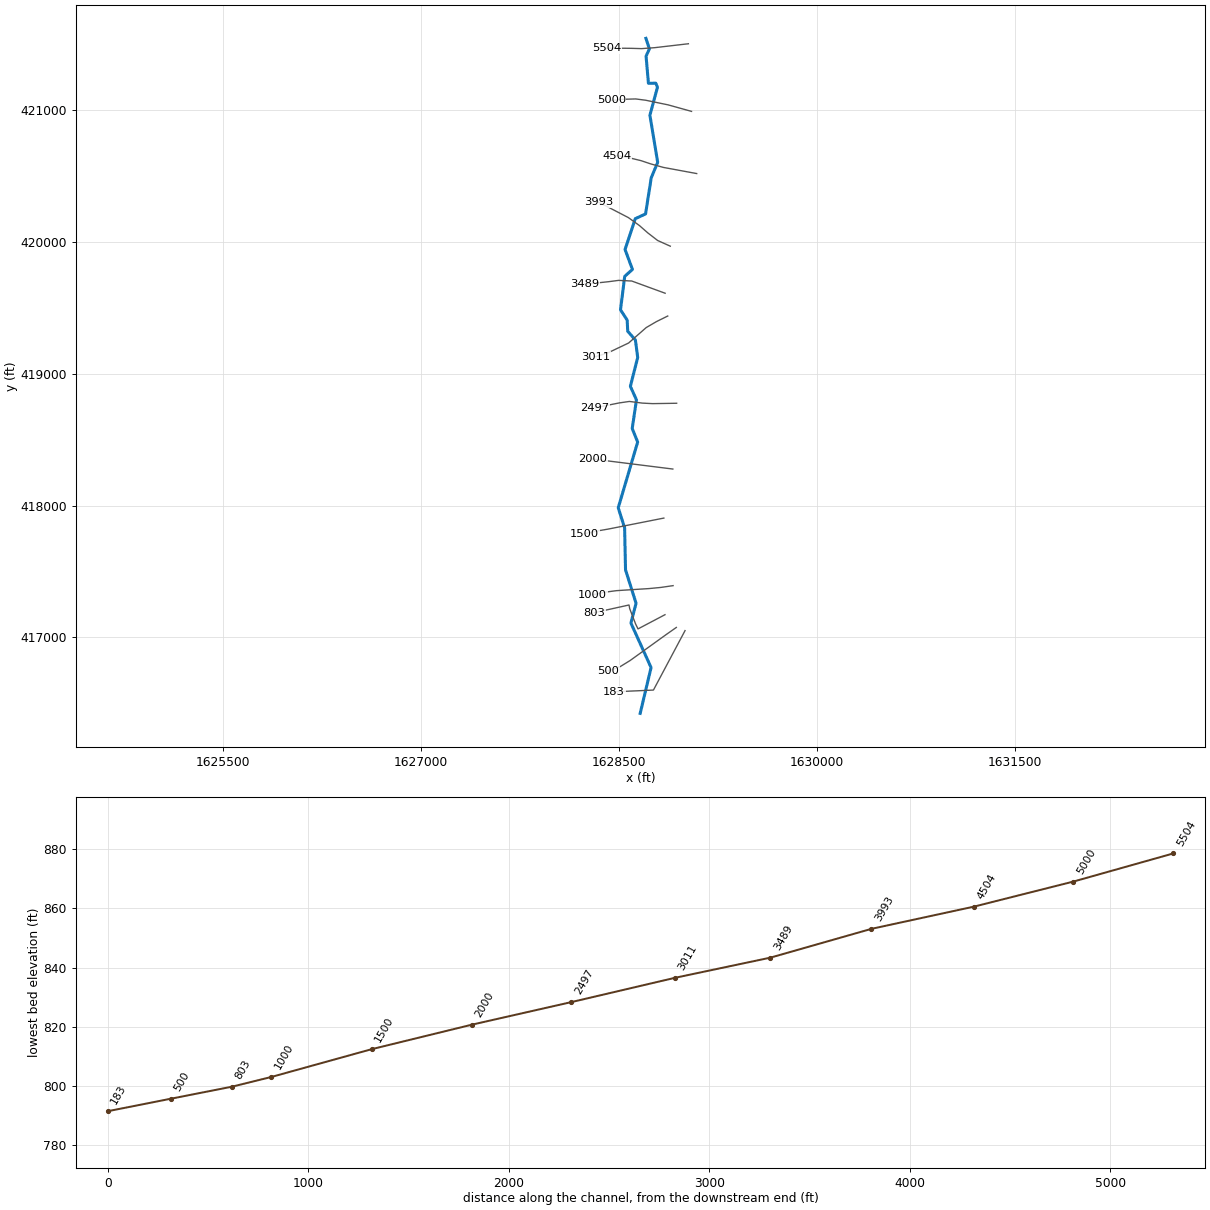
--- LFSCHDLRRN.prj (project) ---

Proj Title=LFSCHDLRRN
Current Plan=p01
Default Exp/Contr=0,0
English Units
Geom File=g01
Flow File=f01
Plan File=p01
BEGIN DESCRIPTION:
---------- MODELED AS PART OF WVEMD CTP PROGRAM, 2023----------
Stream Name: Left Fork Scheiders Run
Flood Zone:  AFH
Wetzel County, WV
HEC-RAS Version: RAS 6.3
Vertical Datum: NAVD88
Projection: NAD 1983 StatePlane West Virginia S FIPS 4702 (US Feet)
Terrain: 1-meter West Virginia FEMA R3 South Central (collected 2018-2020)
Land Use: 2019 NLCD
Hydrologic Method:
WV SIR2010-5033 regression equations
Additional Model Notes:
None
END DESCRIPTION:
DSS Export Rating Curves= 0
DSS Export Rating Curve Sorted= 0
DSS Export Volume Flow Curves= 0
DXF OffsetX= 0
DXF OffsetY= 0
DXF ScaleX= 0
DXF ScaleY= 0

--- LFSCHDLRRN.p01 (plan) ---

Plan Title=Floodplain
Program Version=6.30
Short Identifier=Floodplain
Geom File=g01
Flow File=f01
Subcritical Flow
K Sum by GR= 0
Std Step Tol= 0.01
Critical Tol= 0.01
Num of Std Step Trials= 20
Max Error Tol= 0.3
Flow Tol Ratio= 0.001
Split Flow NTrial= 30
Split Flow Tol= 0.02
Split Flow Ratio= 0.02
Log Output Level= 0
Friction Slope Method= 1
Unsteady Friction Slope Method= 2
Unsteady Bridges Friction Slope Method= 1
Parabolic Critical Depth
Global Vel Dist= 0 , 0 , 0
Global Log Level= 0
CheckData=True
Encroach Param=-1 ,0,0, 0
Mapping Interval=1HOUR
Computation Time Step Use Courant=        0
Computation Time Step Use Time Series=    0
Computation Time Step Count To Double=0
Computation Time Step Max Doubling=0
Computation Time Step Max Halving=0
Computation Time Step Residence Courant=0
Run HTab= 0
Run UNet= 0
Run Sediment= 0
Run PostProcess= 0
Run WQNet= 0
Run RASMapper= 0
UNET Theta= 0
UNET Theta Warmup= 0
UNET ZTol= 0
UNET ZSATol= 0
UNET MxIter= 0
UNET Max Iter WO Improvement= 0
UNET MaxInSteps= 0
UNET DtIC= 0
UNET DtMin= 0
UNET MaxCRTS= 0
UNET WFStab= 0
UNET SFStab= 0
UNET WFX= 1
UNET SFX= 1
UNET Gravity=32.17405
UNET 1D Methodology=Finite Difference
UNET DSS MLevel= 1
UNET Pardiso=0
UNET DZMax Abort= 0
UNET Use Existing IB Tables= 0
UNET Froude Reduction=False
UNET Froude Limit= 0
UNET Froude Power= 0
UNET D1 Cores= 0
UNET WindReference=Eulerian
UNET WindDragFormulation=Hsu (1988)
UNET D2 Coriolis=0
UNET D2 Cores= 0
UNET D2 Theta= 1
UNET D2 Theta Warmup= 1
UNET D2 Z Tol= 0.01
UNET D2 Volume Tol= 0.01
UNET D2 Max Iterations= 20
UNET D2 Equation= 0
UNET D2 RampUpFraction=0.1
UNET D2 TimeSlices= 1
UNET D2 Turbulence Formulation=Non-Conservative (original)
UNET D2 Eddy Viscosity=0.3
UNET D2 Transverse Eddy Viscosity=0.1
UNET D2 Smagorinsky Mixing=0
UNET D2 BCVolumeCheck=0
UNET D2 Cores=0
UNET D2 SolverType=PARDISO (Direct)
UNET D2 Minimum Iterations= 3
UNET D2 Maximum Iterations= 30
UNET D2 Restart Number= 10
UNET D2 Relaxation Coeff=1.3
UNET D2 SOR Precondition Iterations= 10
UNET D2 ILUT Maximum Fill= 8
UNET D2 ILUT Tolerance=1E-08
UNET D2 Convergence Tolerance=0.00001
UNET D1D2 MaxIter= 0
UNET D1D2 ZTol=0.01
UNET D1D2 QTol=0.1
UNET D1D2 MinQTol=1
Write IC File= 0
Write IC File at Fixed DateTime=0
Write IC File at Sim End=0
Echo Input=False
Echo Parameters=False
Echo Output=False
Write Detailed= 0
HDF Write Warmup=0
HDF Write Time Slices=0
HDF Flush=0
HDF Compression= 1
HDF Chunk Size= 1
HDF Spatial Parts= 1
HDF Use Max Rows=0
HDF Fixed Rows= 1
Calibration Method= 0
Calibration Iterations= 20
Calibration Max Change=0.05
Calibration Tolerance=0.2
Calibration Maximum=1.5
Calibration Minimum=0.5
Calibration Optimization Method= 1
WQ AD Non Conservative
WQ ULTIMATE=-1
WQ Max Comp Step=1HOUR
WQ Output Interval=15MIN
WQ Output Selected Increments= 0
WQ Output face flow=0
WQ Output face velocity=0
WQ Output face area=0
WQ Output face dispersion=0
WQ Output cell volume=0
WQ Output cell surface area=0
WQ Output cell continuity=0
WQ Output cumulative cell continuity=0
WQ Output face conc=0
WQ Output face dconc_dx=0
WQ Output face courant=0
WQ Output face peclet=0
WQ Output face adv mass=0
WQ Output face disp mass=0
WQ Output cell mass=0
WQ Output cell source sink temp=0
WQ Output nsm pathways=0
WQ Output nsm derived pathways=0
WQ Create Restart=0
WQ Fixed Restart=0
WQ System Summary=0
WQ Write To DSS=0
Sorting and Armoring Iterations= 10
XS Update Threshold= 0.02
Bed Roughness Predictor= 0
Hydraulics Update Threshold= 0.02
Energy Slope Method= 1
Volume Change Method= 1
Sediment Retention Method= 0
Sediment TS Multiplier= 1
Warm Up Method= 0
XS Weighting Method= 0
Number of US Weighted Cross Sections= 1
Number of DS Weighted Cross Sections= 1
Upstream XS Weight=0
Main XS Weight=1
Downstream XS Weight=0
Number of DS XS's Weighted with US Boundary= 1
Upstream Boundary Weight= 1
Weight of XSs Associated with US Boundary= 0
Number of US XS's Weighted with DS Boundary= 1
Downstream Boundary Weight= 0.5
Weight of XSs Associated with DS Boundary= 0.5
Percentile Method= 0
Sediment Output Level= 3
Mass or Volume Output= 0
Output Increment Type= 1
Profile and TS Output Increment= 1
Transport Output Increment 1
XS Output Flag= 0
XS Output Increment= 10
Read HDF5 Sediment Hotstart= 0
Sediment Hotstart Type= 0
Write Gradation File= 0
Read Gradation Hotstart= 0
Write HDF5 File= 1
Write Binary Output= 1
Write DSS Sediment File= 0
DSS Sediment Output Type= 1
SV Curve= 0
Specific Gage Flag= 0
Subcell Erosion Methods= 0
Subcell Deposition Methods= 0
Advection Scheme= 1
Matrix Solver= 0
Implicit Weighting Factor= 1
Maximum Outer Loop Convergence Iterations= 5
Convergence Maximum Absolute= 0.001
Convergence RMSE= 0.0001
Grain Fractions Max Abs Error= 0.001
Max Subgrid Regions= 1
Max Subgrid Length Scale= 3.402823E+38
Initial Layer Thickness= 3.402823E+38
Min Layer Thickness= 3.402823E+38
Max Layer Thickness= 3.402823E+38
Number of Layers= 5

--- LFSCHDLRRN.f01 (steady flow) ---

Flow Title=Flow
Program Version=6.30
Number of Profiles= 1
Profile Names=F01pct
River Rch & RM=River 1,Reach 1         ,5504
     567
River Rch & RM=River 1,Reach 1         ,3489
     693
River Rch & RM=River 1,Reach 1         ,1000
     786
Boundary for River Rch & Prof#=River 1,Reach 1         , 1
Up Type= 0
Dn Type= 3
Dn Slope=0.0133
DSS Import GetInterval= 0
DSS Import GetPeak= 0
DSS Import FillOption= 0

--- LFSCHDLRRN.g01 (geometry) ---

Geom Title=Geometry
Program Version=6.31

River Reach=River 1         ,Reach 1
Reach XY= 30
1628704.18373255421541.7054428911628730.47894603421461.808770739
1628705.40584297421406.4504640551628723.20337956 421200.80851229
1628778.89224455421201.6447713081628791.74851805421170.789846137
1628734.40742539420958.9753091481628793.42338347420601.682716638
1628744.46711655420484.393581137 1628701.3756673420210.414142221
1628623.63664955420174.6015498041628545.89763181419941.093158558
1628602.09108897419789.9822403041628543.56824014 419737.28287065
1628511.54107322419483.9756344711628562.20238923419405.654268816
1628566.27849655419321.2184140531628624.51033548419254.543350562
1628641.97978872419122.6489293131628586.36867946418903.989917815
1628632.37154022418801.2112519741628600.34404522418584.007290065
1628641.68845072418481.5199622211628494.36262989417983.058032647
 1628542.6948823417830.7824185641628549.68272921417512.547162637
1628629.45980063417259.239598393 1628590.4447868417109.293704063
1628743.30242072416771.8419511471628660.72482997416424.540808484

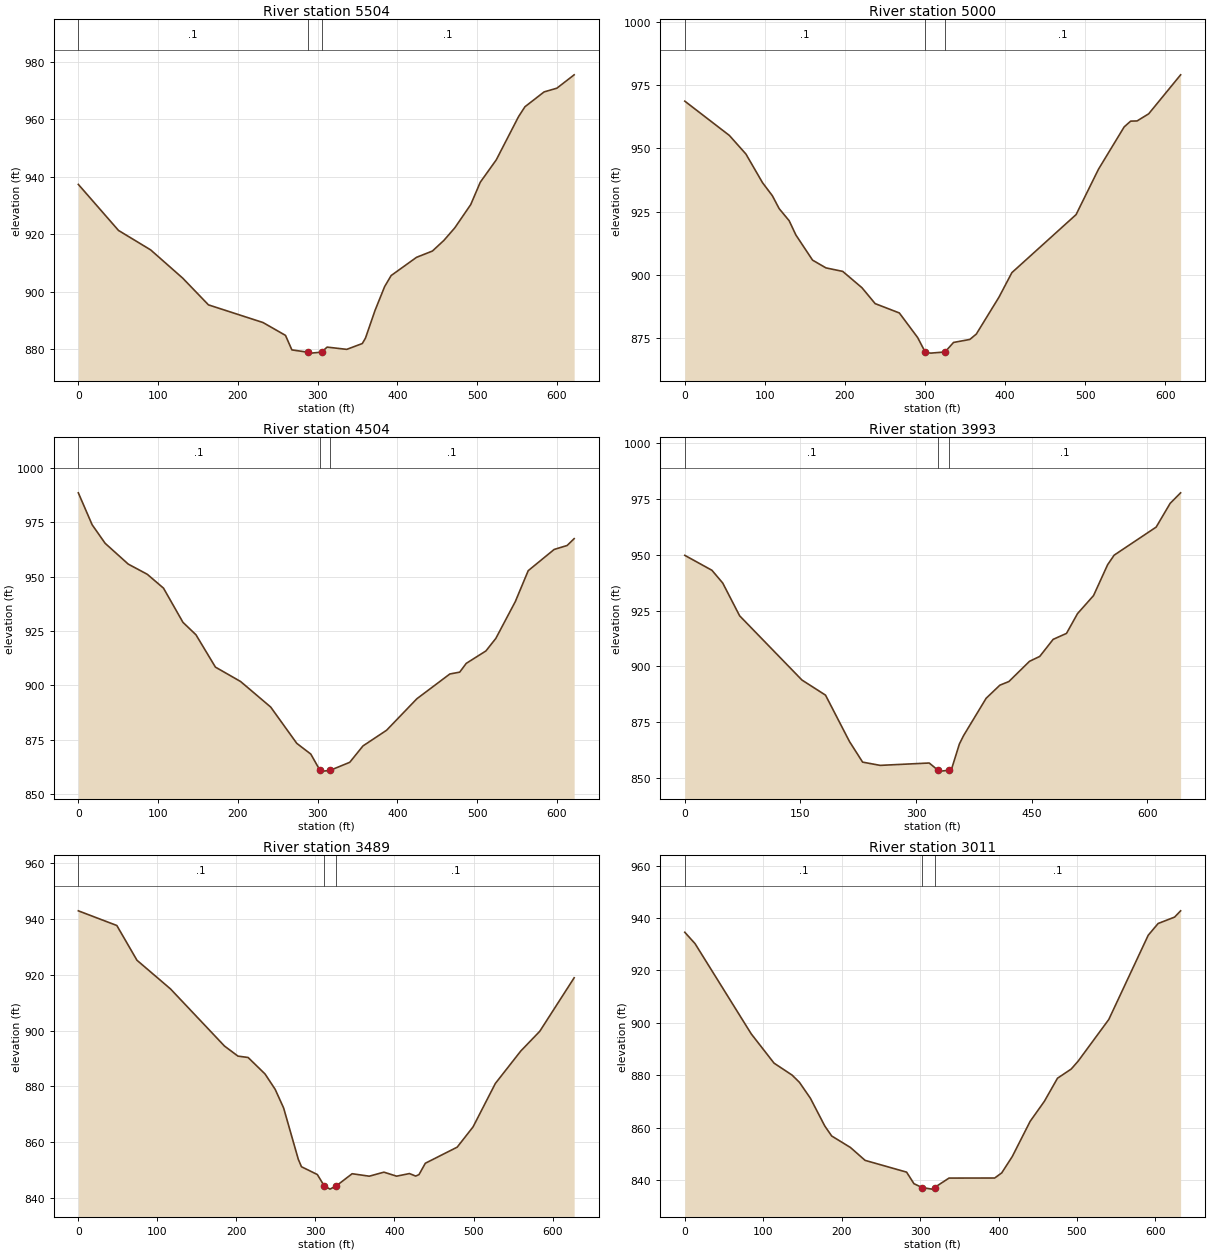
Type RM Length L Ch R = 1 ,5504    ,492.7,498.8,483.8
XS GIS Cut Line= 6
1629026.20933525421500.6458137481628771.67802018421471.016279832
1628671.85702559421463.6790241751628593.55403259421465.941486835
1628502.70578909421466.9342669991628406.38839643421467.148833498
#Sta/Elev= 30
       0  937.27    50.4  921.25    90.7  914.49     131  904.64   163.2  895.37
   231.6  889.23   259.8  884.76   267.8  879.71   287.7  878.91   291.9  878.59
     305  878.93     312  880.68   336.6   879.9   356.1  881.92   360.1  883.82
   372.1  893.45   384.1  901.71   392.3  905.57   424.1   911.9   444.1   914.1
   458.5  917.81   472.1  922.15   492.1  930.25   504.1  938.03   524.1  945.79
   552.1  960.85   560.1  964.27   584.1  969.43   600.1  970.72   621.8  975.37
#Mann= 3 ,-1,0
       0      .1       0   287.7    .045       0     305      .1       0
Bank Sta=287.7,305
XS Rating Curve= 0 ,0
Exp/Cntr(USF)=0,0
Exp/Cntr=0.3,0.1

Type RM Length L Ch R = 1 ,5000    ,493.9,495.6,497
XS GIS Cut Line= 6
1629049.92811984420987.9732826651628872.65288384421037.300611839
1628701.25854158421072.6719321761628626.70882192421082.287070423
1628537.49410534 421079.719490261628441.87257743421071.611566842
#Sta/Elev= 30
       0  968.68    55.7  955.12    76.4  947.76    97.1  936.45   109.4  931.29
   117.9  926.19   130.4   921.4   138.8  915.76   159.6  905.84   176.3  902.77
   197.3  901.38   221.4   894.9   237.8  888.64     268  884.95   290.9  875.23
   300.3   869.5   307.2  869.07   325.1  869.53   335.7  873.29   356.1  874.48
   364.2  876.62   392.5   891.2   408.6  900.89   488.8  923.83   516.8  941.78
   548.9  958.51     557  960.78     565  960.86   579.5  963.67   619.4  979.09
#Mann= 3 ,0,0
       0      .1       0   300.3    .045       0   325.1      .1       0
Bank Sta=300.3,325.1
XS Rating Curve= 0 ,0
Exp/Cntr(USF)=0,0
Exp/Cntr=0.3,0.1

Type RM Length L Ch R = 1 ,4504    ,512.1,511.7,506.9
XS GIS Cut Line= 6
1629089.14031176420516.6021781711628837.15033017420563.132268846
1628740.40905385 420589.934708671628667.63164034420614.341155916
  1628579.602945420635.7508900021628483.50175926420653.152758092
#Sta/Elev= 30
       0  988.65    17.3  973.97    33.6  965.43    62.6  955.85    86.5  951.16
   106.8  944.79   131.2  929.05   147.5  923.33   171.9  908.46   203.4  901.85
   241.2  890.08   273.9  873.38   291.5  868.43     303  860.96     307   860.6
   315.4  860.91   340.3  864.65   356.9  872.19   386.5   879.4   424.4  893.87
   465.8  905.29   478.2  906.15   486.4  910.18   511.1  915.91   523.5  921.67
   547.9  938.59   564.1  952.83   596.6  962.59   612.9  964.42   621.7  967.56
#Mann= 3 ,-1,0
       0      .1       0     303    .045       0   315.4      .1       0
Bank Sta=303,315.4
XS Rating Curve= 0 ,0
Exp/Cntr(USF)=0,0
Exp/Cntr=0.3,0.1

Type RM Length L Ch R = 1 ,3993    ,497.4,504.1,505.8
XS GIS Cut Line= 6
1628888.96026592419966.0957332551628793.01885676420009.295450002
1628717.59709159420067.5984830111628654.77208601 420122.69581376
1628571.50552025420182.6832265851628344.01811434420300.639027417
#Sta/Elev= 30
       0  949.83    35.2  943.13    49.2  937.41    71.1  922.73   151.9  893.93
   182.5  887.15   213.6  866.33   230.6  857.12   253.3  855.66     317  856.72
   328.3  853.49   331.8  853.08     342  853.43   346.5  854.62   356.1  865.25
   361.3  868.87   390.8  885.75   408.6  891.62   420.3  893.25     447  902.31
   460.3  904.51   477.7  912.16     495  914.83   509.3   923.7   530.1   931.8
   548.3  945.61   556.8  949.91   611.3   962.5   629.4  973.13     643  977.86
#Mann= 3 ,-1,0
       0      .1       0   328.3    .045       0     342      .1       0
Bank Sta=328.3,342
XS Rating Curve= 0 ,0
Exp/Cntr(USF)=0,0
Exp/Cntr=0.3,0.1

Type RM Length L Ch R = 1 ,3489    ,469.1,477.3,481.6
XS GIS Cut Line= 6
1628850.00955643419609.3972996771628597.06058726419701.970933422
1628497.06045917419706.9203985931628422.06126533419696.977505088
1628334.56176843 419687.588088171628240.71845217419679.692434669
#Sta/Elev= 30
       0  942.75    48.7  937.51    74.2  925.09   116.7  914.83   184.9  894.45
   201.9  890.86   214.8  890.36   236.2  884.48     249  879.01   259.7  872.35
   278.3     854   282.3  851.34   302.4  848.55   310.9  844.59   318.4  843.34
   326.6  844.55   346.4  848.84   368.1  847.96   386.6   849.4   402.7  847.97
   418.9   848.9   426.9     848     431  848.53     439  852.58   479.3  858.33
   499.4  865.57   527.6  881.08   559.7  892.65   583.8  899.72   627.3  918.83
#Mann= 3 ,-1,0
       0      .1       0   310.9    .045       0   326.6      .1       0
Bank Sta=310.9,326.6
XS Rating Curve= 0 ,0
Exp/Cntr(USF)=0,0
Exp/Cntr=0.3,0.1

Type RM Length L Ch R = 1 ,3011    ,520.9,514.7,508
XS GIS Cut Line= 6
1628869.51017359419436.6581438331628783.63239259419394.158228844
1628706.37664159419349.0904055831628573.20925701419232.258946344
1628418.80503826 419158.647545011628324.76191926419129.008824751
#Sta/Elev= 30
       0  934.59    13.1  930.24    84.7   895.8   113.8  884.61   136.9  880.03
   146.2  877.27   160.1  871.23   178.5  860.61   187.3  856.79   211.1  852.43
   229.9  847.48   282.8  842.99   292.2  838.57   302.6   837.1   314.9   836.5
   318.4837.0992   336.9  840.72   395.1  840.74   404.1   842.7   417.6  848.97
   440.3  862.37   458.5  870.05   475.2  878.85   492.7  882.36   501.5  885.36
   540.6  901.28   590.9  933.46   603.5  937.94   624.5  940.38   632.2  942.78
#Mann= 3 ,-1,0
       0      .1       0   302.6    .045       0   318.4      .1       0
Bank Sta=302.6,318.4
XS Rating Curve= 0 ,0
Exp/Cntr(USF)=0,0
Exp/Cntr=0.3,0.1

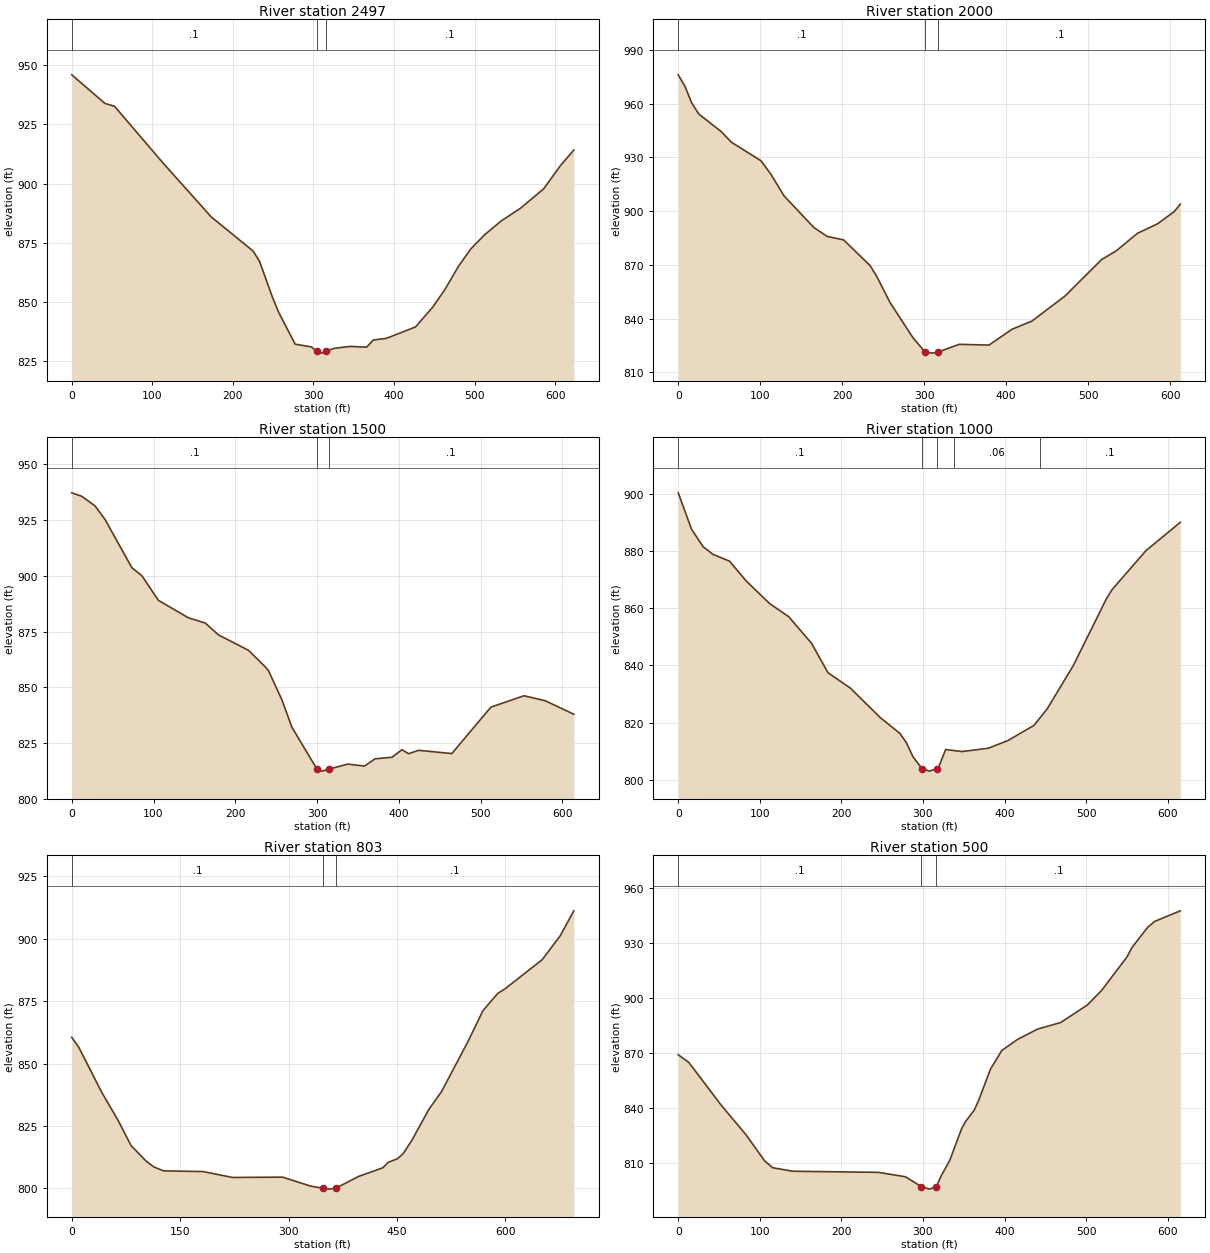
Type RM Length L Ch R = 1 ,2497    ,495.6,496.5,494.4
XS GIS Cut Line= 6
1628937.22887017418775.3651750831628754.63638759418772.589590088
1628679.07125001418776.3992937511628578.69809118418789.096118748
1628502.27599992418778.0039493441628319.36986968418741.300282583
#Sta/Elev= 30
       0  945.96    41.1  933.89    53.1  932.66   113.1  908.76   173.1  885.91
   225.2  871.45   233.2  867.05   249.2  851.89   257.2  845.32   277.4  832.09
   297.6  830.94  304.04829.0285   309.6  828.32  315.08829.0167   325.5  830.33
   345.9  831.17   366.1  830.83   374.2  833.86   390.5  834.55   426.7  839.38
   448.2  847.78   463.5  855.34   480.1  865.05   495.6  872.47   512.7  878.39
   533.1  884.19     557  889.55   585.9  897.79   606.5  907.53   623.3  914.17
#Mann= 3 ,-1,0
       0      .1       0  304.04    .045       0  315.08      .1       0
Bank Sta=304.04,315.08
XS Rating Curve= 0 ,0
Exp/Cntr(USF)=0,0
Exp/Cntr=0.3,0.1

Type RM Length L Ch R = 1 ,2000    ,497.5,500,501.6
XS GIS Cut Line= 6
1628908.30832434418276.7247681771628815.28226367418288.353353843
1628554.80968751418320.9143123331628480.38890459418330.217771426
1628393.56493126418341.0720804181628300.53854251418352.700009927
#Sta/Elev= 30
       0  976.16     8.3  969.68    16.3  960.54    25.1  954.24    52.6   944.4
    64.7  938.57     101  928.14   113.1  920.58   129.2  908.47   165.5  890.85
   181.6  885.91   201.8  883.93     234  869.61   242.1  863.63   258.4  848.96
   286.4  829.25     301  821.34   310.6  820.68  317.34821.3347   342.8   825.6
   379.1  825.18   407.3  834.03   431.5  838.59   471.8  852.56   516.4  872.93
   533.9  877.67   560.5  887.71   584.7  892.91   604.9  899.68   612.5   903.9
#Mann= 3 ,-1,0
       0      .1       0     301    .045       0  317.34      .1       0
Bank Sta=301,317.34
XS Rating Curve= 0 ,0
Exp/Cntr(USF)=0,0
Exp/Cntr=0.3,0.1

Type RM Length L Ch R = 1 ,1500    ,498.4,500,496.5
XS GIS Cut Line= 6
1628840.19461542417905.0168501731628588.81519692417855.293852508
 1628490.7156556417835.8900199231628417.14132768417821.336571336
1628330.85245825417806.5580575911628237.74470484417786.583031923
#Sta/Elev= 30
       0  937.25    12.3  935.68    28.6  931.33    40.9  925.18    73.5  903.66
    85.7  900.07     106  888.99   142.8  881.15   163.2  878.84   179.5   873.5
   216.2  866.58   236.6  859.19   240.7  857.33     257  844.38   269.2   832.1
     300  813.21   305.9  812.39     314  813.22   337.5  815.55   357.9  814.65
   371.1  817.93   391.5  818.61   403.8     822   411.9   820.2   424.1  821.73
   464.8  820.27   512.5  841.09   553.1  846.21   578.9  843.98     614  837.91
#Mann= 3 ,-1,0
       0      .1       0     300    .045       0     314      .1       0
Bank Sta=300,314
XS Rating Curve= 0 ,0
Exp/Cntr(USF)=0,0
Exp/Cntr=0.3,0.1

Type RM Length L Ch R = 1 ,1000    ,203.1,196.6,184.4
XS GIS Cut Line= 6
1628910.29060385417392.8495674281628816.53422968417379.207206249
1628728.76012701417370.6927875881628479.27112468417354.680024341
1628392.27982885 417342.860822261628299.63204826417323.043604672
#Sta/Elev= 30
       0  900.35    16.3  887.64    30.5   881.5    42.6  878.82    62.8  876.47
      83  869.61   112.2  861.57   135.4  857.04   163.5  847.69   183.6  837.42
     211  832.05   247.7  821.72   271.7  816.21   279.7  812.95   287.8  808.02
  298.82  803.89   307.8     803  317.24 803.894   319.8  804.79   327.8  810.54
   347.9  809.85     380     811   404.1  813.69   436.1     819   452.3  824.77
   484.6  840.08     525  863.34   531.8  866.48   573.4  880.13   615.5  890.04
#Mann= 5 ,-1,0
       0      .1       0  298.82    .045       0  317.24      .1       0
  337.94     .06       0  442.94      .1       0
Bank Sta=298.82,317.24
XS Rating Curve= 0 ,0
Exp/Cntr(USF)=0,0
Exp/Cntr=0.3,0.1

Type RM Length L Ch R = 1 ,803     ,293.4,303.4,319.4
BEGIN DESCRIPTION:
Low water crossing
END DESCRIPTION:
XS GIS Cut Line= 6
1628848.68020435417172.562306168 1628644.2130972417064.832324985
1628625.52524332417103.3073182651628581.55382243417217.633012582
1628576.05739482417246.214436161  1628313.328155 417187.95230348
#Sta/Elev= 30
       0  860.48     9.7  856.49    41.3  838.55    63.9  827.34      82  817.16
     103  810.89   113.7  808.57   127.2  807.02   181.5  806.74   222.5  804.38
   291.6  804.51   330.9  800.88   348.1  800.06   355.8  799.71   365.2  800.07
   396.7  804.78   430.2  808.24   437.7  810.41   450.3  811.84   458.2  813.81
   470.5  819.24   493.9  831.57   511.5  838.74   548.4  858.93   568.8  871.13
   589.3  878.06   599.5  879.91   650.8  891.57   675.4  900.98   694.6  911.12
#Mann= 3 ,-1,0
       0      .1       0   348.1    .045       0   365.2      .1       0
Bank Sta=348.1,365.2
XS Rating Curve= 0 ,0
Exp/Cntr(USF)=0,0
Exp/Cntr=0.3,0.1

Type RM Length L Ch R = 1 ,500     ,321.2,316.7,310.7
XS GIS Cut Line= 6
  1628934.767589 417075.951251091628857.96360876 417022.17642425
1628644.93680385416868.7951693391628584.07242426416824.971438095
1628509.31502783 416779.067330421628418.39362176416746.596266761
#Sta/Elev= 30
       0  868.89      13  864.71    52.1  841.72    82.7   825.5   105.9  811.07
   115.8  807.32   140.4  805.41   245.3   804.8   278.4  802.41   298.1  797.02
     308  795.66  316.42797.0332   322.6  803.12   332.6  811.03   347.4  828.56
   352.3  832.57   362.8  838.66   368.5  844.24   382.8  861.09   396.7  871.23
   416.4  877.37   440.6  882.87   468.8  886.45   501.6  896.01     519  903.93
   550.1  922.18   556.3  927.37   575.5  938.34     584  941.55   615.5  947.32
#Mann= 3 ,-1,0
       0      .1       0   298.1    .045       0  316.42      .1       0
Bank Sta=298.1,316.42
XS Rating Curve= 0 ,0
Exp/Cntr(USF)=0,0
Exp/Cntr=0.3,0.1

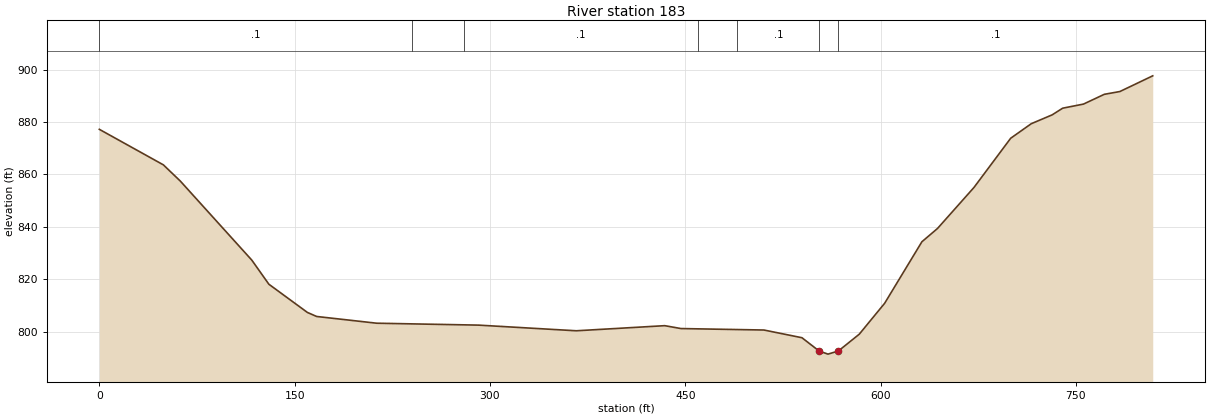
Type RM Length L Ch R = 1 ,183     ,,,
XS GIS Cut Line= 3
1629000.81773509417051.9498580991628761.22342068416601.244469451
 1628462.9871412416587.840591721
#Sta/Elev= 30
       0  877.22    49.2  863.65    62.2  857.46   117.1  827.29   130.2  818.09
   159.8  807.32   166.9  805.78     213  803.21   291.2  802.48   366.3  800.32
   434.2  802.27   446.7  801.17   510.4  800.61   539.6  797.67   552.8  792.59
   559.6  791.41   567.6  792.62   583.6  799.01   603.1  810.81   631.7  834.29
   643.7  839.37   671.7  855.02   699.9  873.81   715.7  879.36   731.8  882.75
   739.8  885.28   755.8  886.85   771.8  890.58   783.8  891.65     809  897.64
#Mann= 7 ,-1,0
       0      .1       0     240     .05       0     280      .1       0
     460     .06       0     490      .1       0   552.8    .045       0
   567.6      .1       0
Bank Sta=552.8,567.6
XS Rating Curve= 0 ,0
Exp/Cntr(USF)=0,0
Exp/Cntr=0.3,0.1
LCMann Table=0

Chan Stop Cuts=-1
Use User Specified Reach Order=0
Composite Channel Slope=5